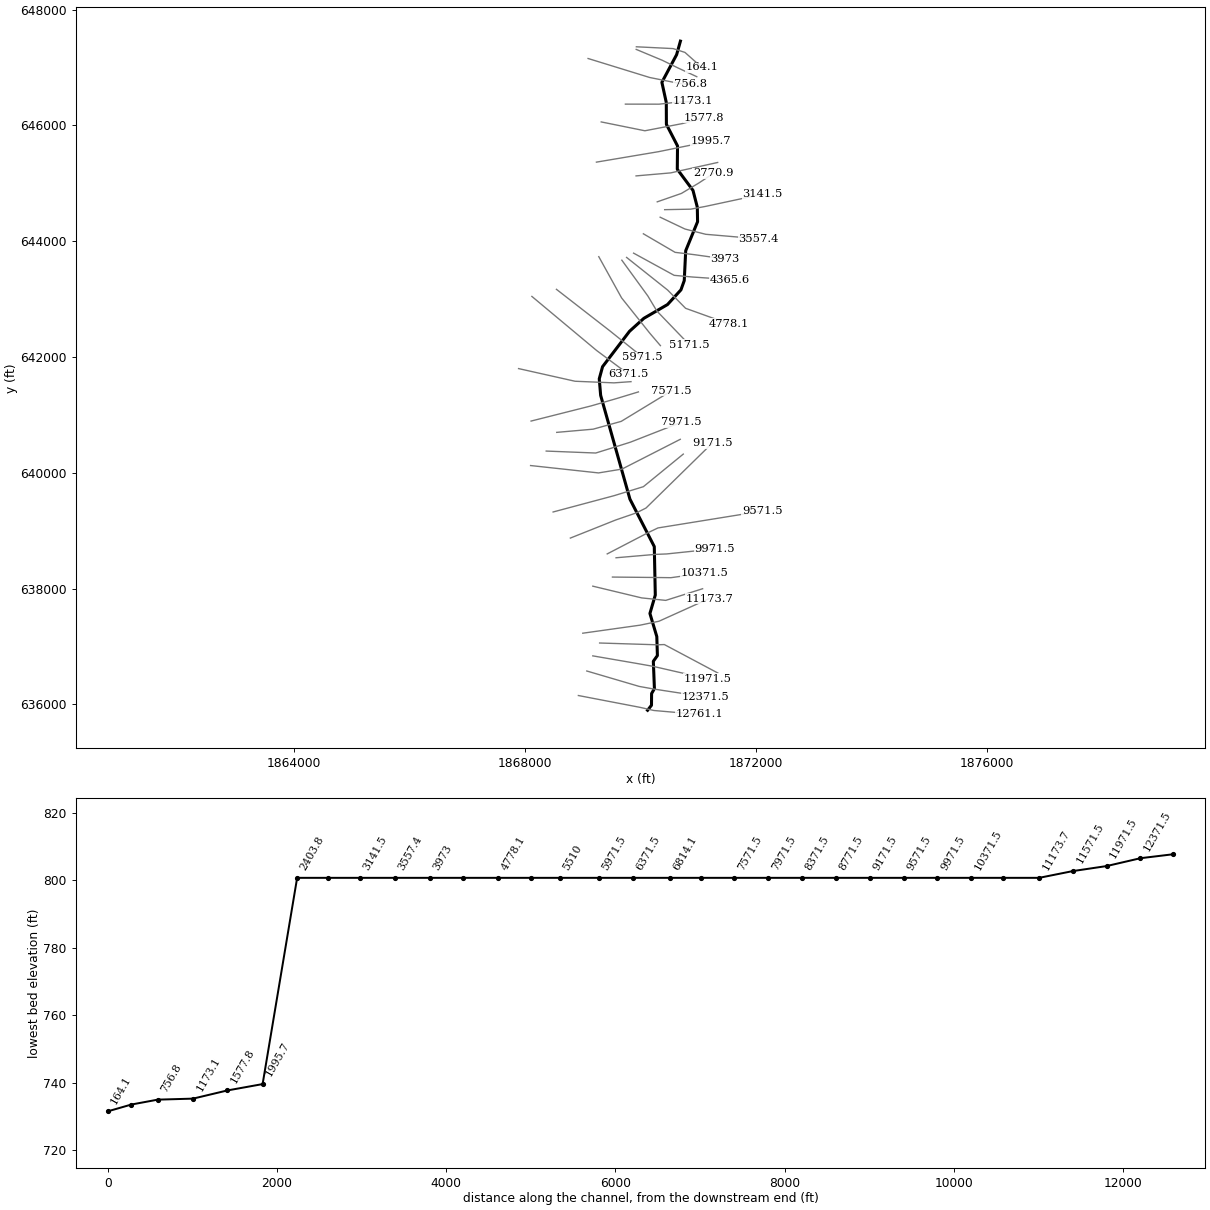
--- CharlesFrk.prj (project) ---

Proj Title=CharlesFrk
Current Plan=p01
Default Exp/Contr=0,0
English Units
Geom File=g01
Flow File=f01
Plan File=p01
BEGIN DESCRIPTION:
AMEC Environment & Infrastructure, 2013
Projection: NAD 1983 State Plane West Virginia South FIPS 4702 (US Feet)
Vertical Datum: NAVD 1988
END DESCRIPTION:
DSS Export Rating Curves= 0
DSS Export Rating Curve Sorted= 0
DSS Export Volume Flow Curves= 0
DXF OffsetX= 0
DXF OffsetY= 0
DXF ScaleX= 0
DXF ScaleY= 0

--- CharlesFrk.p01 (plan) ---

Plan Title=Floodplain
Program Version=4.00
Geom File=g01
Flow File=f01
K Sum by GR=0
Std Step Tol=0.01
Critical Tol=0.01
Num of Std Step Trials=20
Max Error Tol=0.3
Flow Tol Ratio=0.001
Split Flow NTrial=30
Split Flow Tol=0.02
Split Flow Ratio=0.02
Log Output Level=0
Friction Slope Method=1
Unsteady Friction Slope Method=2
Unsteady Bridges Friction Slope Method=1
Global Log Level=0
CheckData=False
Run HTab=0
Run UNet=0
Run PostProcess=0
UNET Theta=0
UNET Theta Warmup=0
UNET ZTol=0
UNET ZSATol=0
UNET MxIter=0
UNET MaxInSteps=0
UNET DtIC=0
UNET DtMin=0
UNET MaxCRTS=0
UNET WFStab=0
UNET SFStab=0
UNET WFX=0
UNET SFX=0
UNET DSS MLevel=0
UNET DZMax Abort=0
UNET Convert EG Bridges=0
UNET Use Existing IB Tables=0
UNET Froude Limit=0
UNET Froude Power=0
Write IC File=0
Echo Input=False
Echo Output=False
Write Detailed=0

--- CharlesFrk.f01 (steady flow) ---

Flow Title=NFF Regression Equation
Program Version=4.10
Number of Profiles= 1
Profile Names=P100yr
River Rch & RM=CharlesFrk,Main            ,12761.1
818.4444
River Rch & RM=CharlesFrk,Main            ,12371.5
903.6022
River Rch & RM=CharlesFrk,Main            ,11173.7
927.2205
River Rch & RM=CharlesFrk,Main            ,10748.2
1082.475
River Rch & RM=CharlesFrk,Main            ,9171.5
1146.894
River Rch & RM=CharlesFrk,Main            ,7571.5
1225.039
River Rch & RM=CharlesFrk,Main            ,4778.1
1350.209
River Rch & RM=CharlesFrk,Main            ,2403.8
1403.523
River Rch & RM=CharlesFrk,Main            ,1995.7
1415.503
River Rch & RM=CharlesFrk,Main            ,444.6
1486.385
River Rch & RM=CharlesFrk,Main            ,164.1
 1488.72
Boundary for River Rch & Prof#=CharlesFrk,Main            , 1
Up Type= 0
Dn Type= 3
Dn Slope=0.0072
DSS Import GetInterval= 0
DSS Import GetPeak= 0
DSS Import FillOption= 0

--- CharlesFrk.g01 (geometry) ---

Geom Title=USGS 3m DEM
Program Version=4.10

River Reach=CharlesFrk      ,Main
Reach XY= 30
     1870126.377       635897.78     1870194.106       635984.62
     1870195.834      636186.826     1870244.832      636271.339
     1870226.046      636743.945     1870296.534      636842.575
     1870286.177      637170.506     1870166.951      637569.691
     1870260.014      637888.092     1870242.608      638725.201
      1869820.54      639544.924     1869313.326       641337.22
     1869288.998      641622.045     1869346.301      641832.194
     1869813.456      642443.551       1870061.8      642667.603
     1870471.661      642905.557     1870704.373      643159.133
     1870761.678      643318.916     1870786.909      643835.078
     1870992.617      644336.662     1870987.935       644587.26
     1870913.197      644877.166     1870641.171      645242.262
     1870645.082      645645.484     1870452.407      646017.808
     1870450.652      646394.683     1870374.218      646743.766
     1870629.497      647221.384     1870695.482      647455.308

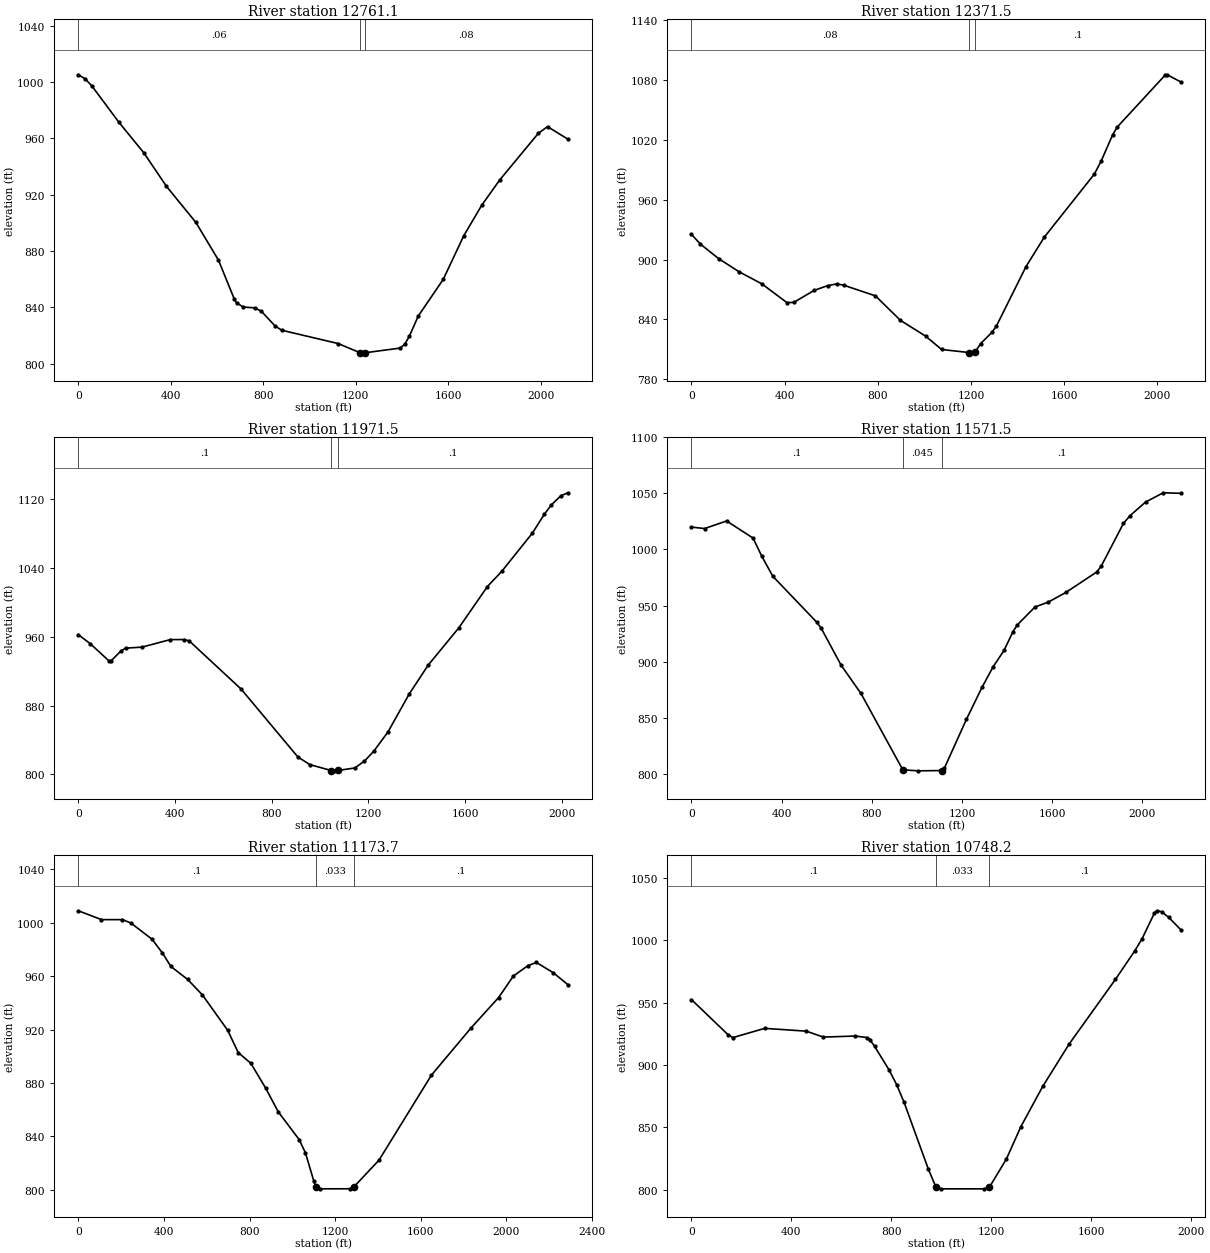
Type RM Length L Ch R = 1 ,12761.1 ,388.4,389.6,390.4
XS GIS Cut Line= 4
     1868927.228      636152.606     1869993.548      635948.729
     1870235.735      635894.041     1871017.506      635826.217
#Sta/Elev= 30
       0 1005.13    29.3 1002.28    58.7  997.19     176  971.31   283.6  949.69
   381.4  925.92   508.6  900.31   606.4  873.53   674.8  845.91   684.6  843.16
     714  840.22   762.9  839.64   792.2   837.2   850.9  826.84   880.2  823.75
  1123.8  814.32    1219  807.78  1228.9   807.7  1238.4   807.7  1392.8  811.09
  1412.4   813.8    1432  819.33  1471.2  833.91  1579.1  859.86  1667.4  890.68
  1745.9  912.56  1824.4  930.64  1991.1  963.66  2030.4  968.31  2118.6  959.41
#Mann= 3 , 0 , 0
       0     .06       0    1219    .045       0  1238.4     .08       0
Bank Sta=1219,1238.4
XS Rating Curve= 0 ,0
Exp/Cntr=0.3,0.1

Type RM Length L Ch R = 1 ,12371.5 ,399.9,400,398.1
XS GIS Cut Line= 4
     1869073.062      636576.217     1869981.124      636309.999
     1870242.308       636263.26     1871121.673      636129.169
#Sta/Elev= 30
       0  925.35      39  915.46   117.1  900.95   204.9  887.72   302.4  875.68
   409.7  856.94     439  856.98   526.8  869.08   585.3  873.89   624.4  875.58
   653.6  874.33   790.2  863.59   897.5     839  1005.2   823.3    1074  809.87
    1192  806.82  1201.8  806.52  1219.1  807.71  1240.9  815.69  1289.8  826.99
  1309.4  833.49  1436.4  893.03  1514.6  922.39  1729.7  985.69    1759   998.8
  1807.9 1024.96  1827.4  1032.7  2032.7 1084.64  2042.5 1085.15  2101.1 1077.89
#Mann= 3 , 0 , 0
       0     .08       0    1192    .045       0  1219.1      .1       0
Bank Sta=1192,1219.1
XS Rating Curve= 0 ,0
Exp/Cntr=0.3,0.1

Type RM Length L Ch R = 1 ,11971.5 ,396.7,400,405.9
XS GIS Cut Line= 4
     1869177.228      636837.502     1869927.775      636708.656
     1870217.713      636657.508     1871163.339      636441.669
#Sta/Elev= 30
       0  962.48    48.8  952.14   126.9  931.96   136.7   932.4   175.7  943.32
   195.3  946.82   263.6  948.01   380.8  956.78   439.3  956.78   458.9  955.26
   673.7  899.21   908.7  820.23   957.8  811.46  1046.1  804.58  1055.9  804.19
  1075.5  804.69  1144.1  807.51  1183.3  815.37  1222.5  826.94  1281.3   849.4
  1369.5   893.7  1447.8  927.13  1575.2  970.69  1692.8 1018.48  1751.6 1035.93
  1878.9 1080.56  1927.9 1102.29  1957.3 1113.34  1996.5 1123.96  2025.9 1127.44
#Mann= 3 , 0 , 0
       0      .1       0  1046.1    .045       0  1075.5      .1       0
Bank Sta=1046.1,1075.5
XS Rating Curve= 0 ,0
Exp/Cntr=0.3,0.1

Type RM Length L Ch R = 1 ,11571.5 ,392,397.8,401.2
XS GIS Cut Line= 4
     1869295.284      637059.724     1870291.215       637028.87
      1870416.78      637032.993     1871343.895      636541.495
#Sta/Elev= 30
       0 1019.95    58.6 1018.63   156.3 1025.38   273.5 1010.16   312.6  993.88
   361.4  976.05   556.8  935.02   576.4   929.6   664.3  896.83   752.2  871.65
   937.8   803.6  1006.1   802.7  1112.4  802.97    1122     805  1220.1  848.62
  1288.8     877  1337.8  895.25  1386.8     910  1426.1  926.59  1445.7   932.8
  1524.1  948.72    1583  953.08  1661.4  961.74  1798.7  980.02  1818.3  985.32
  1916.4 1023.22  1945.8 1030.16  2014.5 1042.23  2092.9 1050.51  2171.4 1050.02
#Mann= 3 , 0 , 0
       0      .1       0   937.8    .045       0  1112.4      .1       0
Bank Sta=937.8,1112.4
XS Rating Curve= 0 ,0
Exp/Cntr=0.3,0.1

Type RM Length L Ch R = 1 ,11173.7 ,432.4,425.5,418.4
XS GIS Cut Line= 4
     1869003.617      637228.995     1869996.673      637367.884
     1870323.497      637435.676     1871191.117      637826.217
#Sta/Elev= 30
       0 1009.06   108.1 1002.44   206.4 1002.41   245.8  999.87   344.1   987.8
   393.2  977.39   432.6  967.33   511.2  957.57     580  945.98     698  919.49
   747.1  902.84   806.1  894.78   874.9  876.33   933.9   858.5  1032.2  837.57
  1061.6  827.52  1100.9   806.3  1110.7  802.08  1130.3   800.7  1267.8  800.75
  1287.4  802.11  1405.2  822.21  1650.4  885.94  1836.8  921.55  1964.3  944.07
  2032.9  960.13  2101.6     968  2140.8  970.32  2219.3  962.68    2288  953.69
#Mann= 3 , 0 , 0
       0      .1       0  1110.7    .033       0  1287.4      .1       0
Bank Sta=1110.7,1287.4
XS Rating Curve= 0 ,0
Exp/Cntr=0.3,0.1

Type RM Length L Ch R = 1 ,10748.2 ,374.7,376.7,378.8
XS GIS Cut Line= 4
     1869177.228      638041.495     1870024.147      637838.652
     1870441.117      637795.835     1871080.006      637997.224
#Sta/Elev= 30
       0  952.53   146.8  924.33   166.4  921.99   293.6  929.39   459.9  927.15
   528.4  922.39   655.6  923.24   704.5  921.98   714.3  920.41   733.9  914.85
   792.6  895.69     822  884.16   851.3  870.23   948.8  816.48   978.1  802.54
   997.6   800.7  1173.1   800.7  1192.6  801.84  1260.8  824.47  1319.2  850.58
  1406.5  882.81  1513.3   917.1  1697.8  968.69  1775.4  991.61  1804.6 1001.38
  1853.1 1021.56  1862.8 1023.68  1882.2 1022.98  1911.4  1018.3  1959.9 1008.34
#Mann= 3 , 0 , 0
       0      .1       0   978.1    .033       0  1192.6      .1       0
Bank Sta=978.1,1192.6
XS Rating Curve= 0 ,0
Exp/Cntr=0.3,0.1

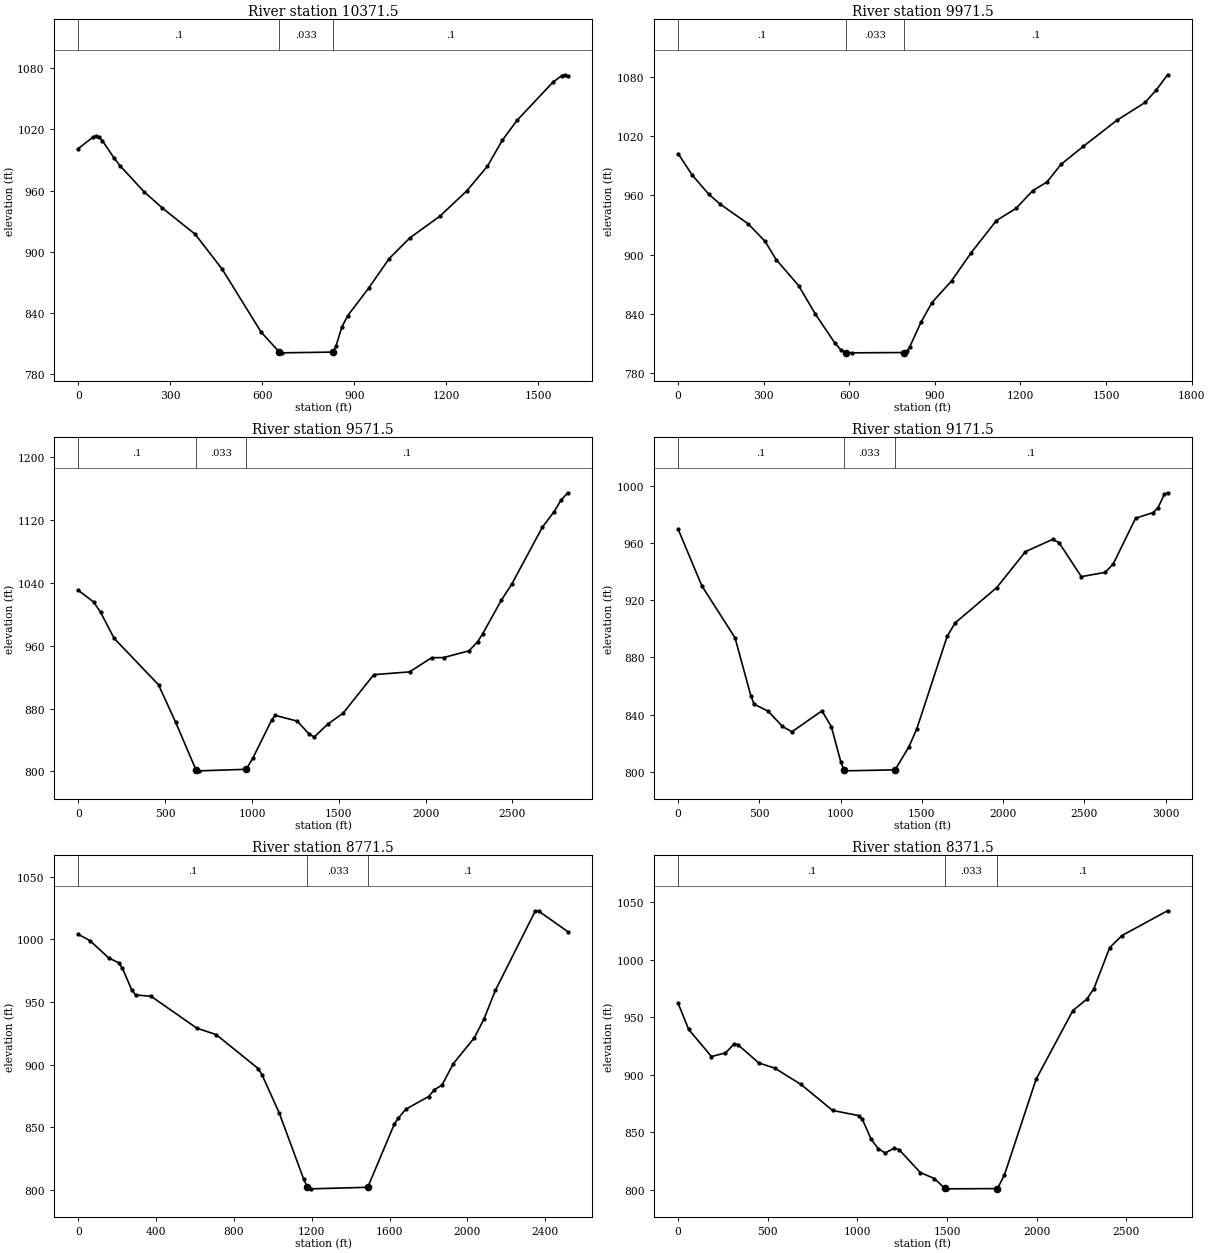
Type RM Length L Ch R = 1 ,10371.5 ,396.7,400,400
XS GIS Cut Line= 4
     1869517.506      638198.613     1870260.634      638191.269
     1870531.264      638187.941     1871107.784      638268.058
#Sta/Elev= 30
       0 1001.23    48.9 1012.59    58.7 1013.35    68.4 1012.16    78.2 1009.03
   117.3  991.55   136.9  984.01   215.1  958.56   273.8   942.9   381.4  916.98
   469.4  882.66   596.5  820.86   655.2  801.57   664.9   800.7   830.2  801.45
   839.8  807.01   859.2  826.03   878.5  837.22   946.2  864.04  1013.8  893.28
  1081.7  913.68  1178.7  934.77    1266  959.46    1334  983.91  1382.4 1009.33
    1431    1029  1547.4 1066.28  1576.5 1072.78  1586.2 1073.58  1595.9 1072.61
#Mann= 3 , 0 , 0
       0      .1       0   655.2    .033       0   830.2      .1       0
Bank Sta=655.2,830.2
XS Rating Curve= 0 ,0
Exp/Cntr=0.3,0.1

Type RM Length L Ch R = 1 ,9971.5  ,391.2,400,409.2
XS GIS Cut Line= 4
     1869580.006      638531.947      1870255.11       638589.94
     1870457.228      638598.034     1871288.339      638684.724
#Sta/Elev= 30
       0 1002.25    49.1  980.67     108  960.94   147.3  951.19   245.5  931.21
   304.4  913.61   343.7  895.05   422.3  868.71   481.2  839.91   549.9   810.4
   569.6     804   589.2     801   608.8   800.7   793.2  801.03   802.8  802.67
   812.4  807.09     851  831.43   889.7  851.53   958.5  873.51  1027.3  902.01
  1115.8  934.53  1184.6  946.88  1243.6  964.88  1292.8  973.48  1341.9  991.27
  1420.6 1009.59  1538.5 1036.04  1636.8 1053.95  1676.2 1066.64  1715.5 1081.95
#Mann= 3 , 0 , 0
       0      .1       0   589.2    .033       0   793.2      .1       0
Bank Sta=589.2,793.2
XS Rating Curve= 0 ,0
Exp/Cntr=0.3,0.1

Type RM Length L Ch R = 1 ,9571.5  ,403.3,400,400.4
XS GIS Cut Line= 4
     1869427.228      638598.787       1870142.6      638969.144
     1870305.482      639046.974     1872114.728       639338.37
#Sta/Elev= 30
       0 1030.38    88.4 1015.56   127.7  1002.6   206.3  969.32   461.7  910.24
     560  862.71   677.8  801.76   697.5   800.7   967.1  802.65  1005.7  817.17
  1113.5  865.38  1133.1  871.32  1260.5  863.97  1329.1   847.4  1358.5  843.85
  1436.9  860.18  1525.1  874.12  1701.5  923.09  1907.3  926.61  2034.7  944.66
  2103.2  944.84  2250.2  953.45  2299.2   964.9  2328.6  975.18  2436.4 1018.05
  2495.2 1037.97  2671.6 1110.48  2740.2 1130.62  2779.4 1145.08  2818.6 1154.54
#Mann= 3 , 0 , 0
       0      .1       0   677.8    .033       0   967.1      .1       0
Bank Sta=677.8,967.1
XS Rating Curve= 0 ,0
Exp/Cntr=0.3,0.1

Type RM Length L Ch R = 1 ,9171.5  ,400.7,400,396.2
XS GIS Cut Line= 5
     1868788.339      638872.224     1869575.145       639184.84
     1869930.938      639306.886     1870098.874      639390.854
     1871244.937      640510.245
#Sta/Elev= 30
       0  969.63     146  929.99   350.3  893.68   447.6  853.26   467.1  847.34
   554.7  842.36   642.3  831.73   700.7  828.02   885.2  842.59   943.1  831.62
    1001  807.21  1020.2  801.56  1029.9   800.7  1335.4  801.39  1420.4  817.42
  1469.5  830.14  1656.2  894.72  1705.4  904.08  1960.9  928.71  2137.8  953.85
  2304.9  962.44  2344.2  960.22  2481.8  936.41  2629.3  939.38  2678.4  945.32
    2816  977.24  2924.1  981.17  2953.6  984.53  2992.9  993.93  3012.6     995
#Mann= 3 , 0 , 0
       0      .1       0  1020.2    .033       0  1335.4      .1       0
Bank Sta=1020.2,1335.4
XS Rating Curve= 0 ,0
Exp/Cntr=0.3,0.1

Type RM Length L Ch R = 1 ,8771.5  ,403,400,404.2
XS GIS Cut Line= 5
     1868489.728      639322.745     1869544.228      639603.889
     1869783.132      639676.955     1870053.714      639759.709
     1870744.937      640322.745
#Sta/Elev= 30
       0 1003.95      59  999.05   157.3  984.99   206.5  981.39   226.1  977.08
   275.3  959.27     295  955.54   373.6  954.51   609.6  928.98   707.9  923.95
   924.2  896.82   943.9  891.86  1032.3  861.38  1158.6  808.31  1177.8  801.86
    1197   800.7  1487.5  801.94  1624.1  852.44  1643.7  857.01  1682.9   864.3
  1800.5  874.43  1829.8  879.84    1869  883.58  1927.8  900.81  2035.6  921.41
  2084.6   936.3  2143.4   959.2  2349.1  1022.8  2368.7 1022.24  2515.6 1006.17
#Mann= 3 , 0 , 0
       0      .1       0  1177.8    .033       0  1487.5      .1       0
Bank Sta=1177.8,1487.5
XS Rating Curve= 0 ,0
Exp/Cntr=0.3,0.1

Type RM Length L Ch R = 1 ,8371.5  ,396.9,400,396
XS GIS Cut Line= 4
     1868099.103      640124.829     1869276.534       639997.34
     1869682.099      640063.493     1870692.853      640577.954
#Sta/Elev= 30
       0   962.2    58.7  939.44     186  915.82   264.3  918.96   313.2  926.86
   332.8  926.19   450.2  910.19   538.3  905.75   685.1  891.56   861.3  868.93
  1008.1   864.4  1027.7  861.12  1076.6   843.8  1115.8  835.67    1155  831.86
  1203.9  836.01  1233.2  834.68  1350.6  814.85  1428.9  809.68  1487.6  801.02
  1497.4   800.7    1781  800.92  1820.1  812.96  1996.1  895.98  2201.4  955.79
  2279.6  965.79  2318.8  974.96  2406.7 1010.55  2475.2  1021.1  2729.4 1042.62
#Mann= 3 , 0 , 0
       0      .1       0  1487.6    .033       0    1781      .1       0
Bank Sta=1487.6,1781
XS Rating Curve= 0 ,0
Exp/Cntr=0.3,0.1

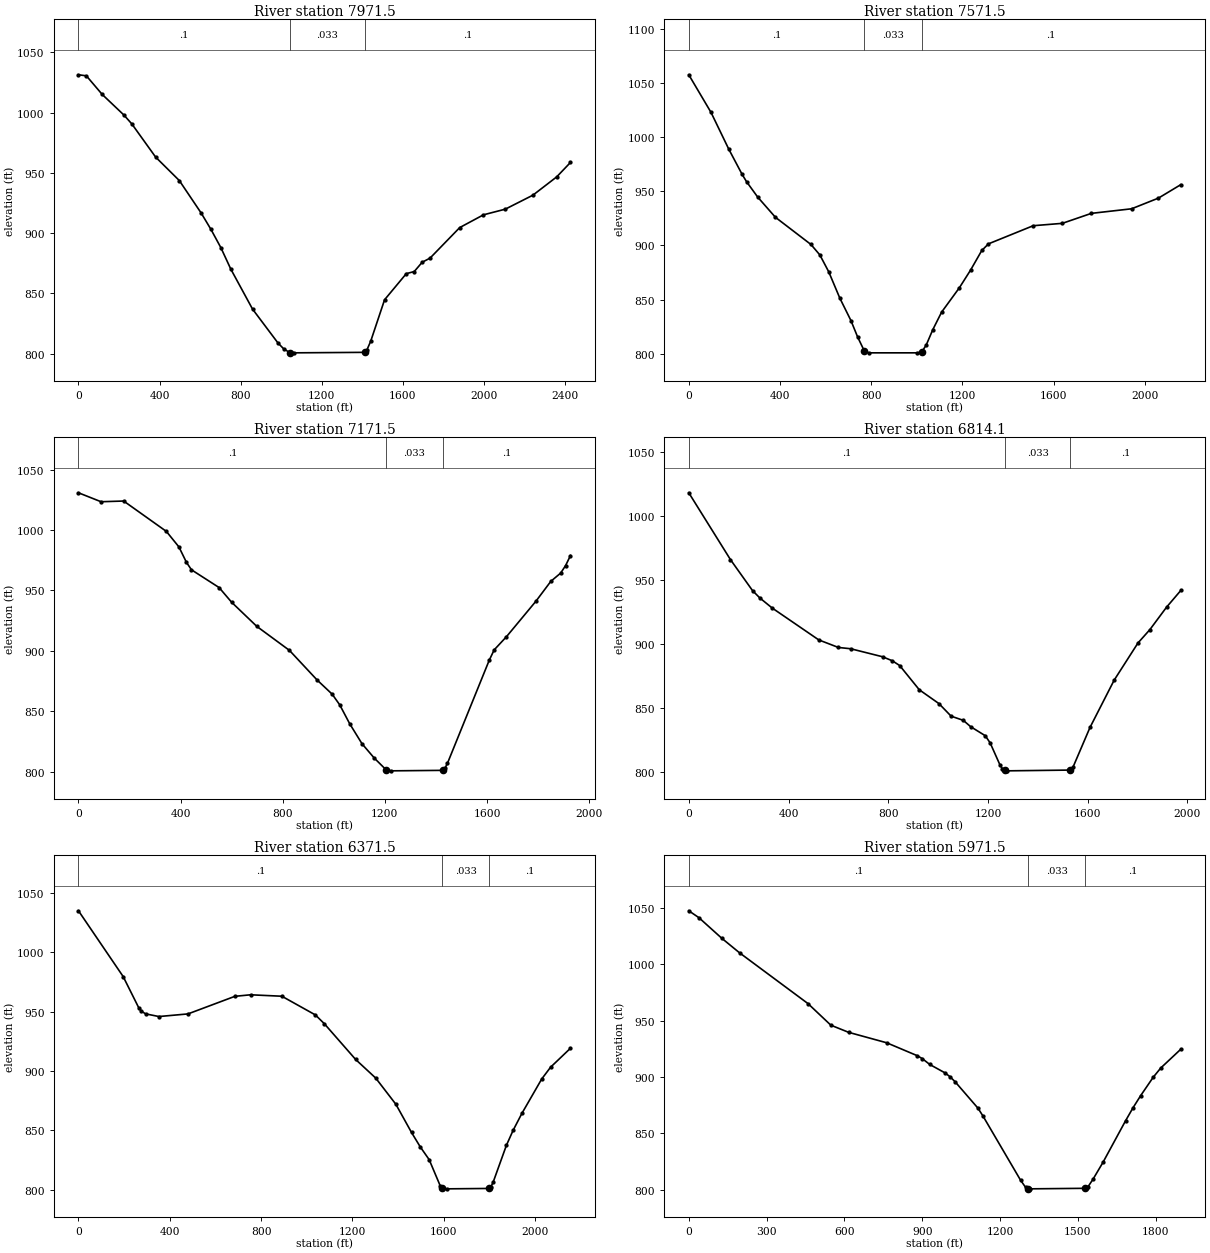
Type RM Length L Ch R = 1 ,7971.5  ,400.6,400,399.3
XS GIS Cut Line= 5
     1868369.937      640374.829     1869227.923       640341.09
     1869560.303      640444.036     1869830.819      640529.156
      1870703.27       640869.62
#Sta/Elev= 30
       0 1031.33      39 1030.47   117.1 1015.03   224.4  997.91   263.4  990.54
   380.5  963.08   497.6  943.57     605  916.71   653.7  903.02   702.5   887.9
   751.3  870.17   858.6  836.97   984.3  808.81  1013.3  803.84  1042.3  800.93
  1061.6   800.7    1412  801.11  1421.8   802.8  1441.3   810.3  1509.7  844.72
    1617   866.4    1656  868.12  1695.1  875.82  1734.1  879.28  1880.4   904.6
  1997.5  915.18  2104.8  919.85  2241.4  931.48  2358.4  946.61  2426.7  958.64
#Mann= 3 , 0 , 0
       0      .1       0  1042.3    .033       0    1412      .1       0
Bank Sta=1042.3,1412
XS Rating Curve= 0 ,0
Exp/Cntr=0.3,0.1

Type RM Length L Ch R = 1 ,7571.5  ,399.8,400,400.3
XS GIS Cut Line= 5
     1868552.228      640697.745     1869183.123      640753.061
     1869455.212      640828.424     1869669.433      640887.758
     1870541.812      641416.495
#Sta/Elev= 30
       0 1057.78    97.4 1023.05   175.4  989.02   233.8  965.76   253.3  958.97
     302  944.78     380  926.02   535.9  900.87   574.8  891.24   613.8  875.64
   662.5  851.26   711.2  830.54   740.4  815.44   769.6  802.58   789.1   800.7
  1002.6   800.7    1022  801.65  1041.3  807.86  1070.3  822.14  1108.9  838.34
    1187  860.93    1236  877.22  1285.1  895.33  1314.5  901.47  1510.7  918.24
  1638.2  920.42  1765.7  929.65  1942.2  933.88    2060  943.77    2158  956.21
#Mann= 3 , 0 , 0
       0      .1       0   769.6    .033       0    1022      .1       0
Bank Sta=769.6,1022
XS Rating Curve= 0 ,0
Exp/Cntr=0.3,0.1

Type RM Length L Ch R = 1 ,7171.5  ,364.6,357.4,350.1
XS GIS Cut Line= 5
     1868107.784      640893.058     1869147.708      641154.822
     1869349.112      641212.707      1869589.06       641281.97
     1869967.506      641396.646
#Sta/Elev= 30
       0 1030.78    88.5 1023.37   177.1 1023.95   344.3  998.82   393.5  985.97
     423   973.2   442.7  967.04   550.9  952.35   600.1  940.15   698.5  920.24
   826.4  900.36   934.6  875.89   993.7  864.13  1023.2  855.34  1062.5  839.61
  1110.5  823.14  1158.1  811.36  1205.7   801.4  1224.8   800.7    1426   801.1
  1435.6  802.97  1445.2  806.94  1608.8   892.2  1628.1  900.77  1676.3  911.69
  1792.1  941.16    1850  957.48  1888.5  964.32  1907.8   970.5  1927.1  978.88
#Mann= 3 , 0 , 0
       0      .1       0  1205.7    .033       0    1426      .1       0
Bank Sta=1205.7,1426
XS Rating Curve= 0 ,0
Exp/Cntr=0.3,0.1

Type RM Length L Ch R = 1 ,6814.1  ,456.1,442.6,429.1
XS GIS Cut Line= 4
     1867891.117      641799.423     1868870.284      641580.673
     1869543.895      641552.896     1869839.034      641573.729
#Sta/Elev= 30
       0 1018.37   167.2  966.04   255.7  941.79   285.2     936   334.4  928.17
   521.3   903.2     600  897.29   649.2  896.28   777.1  890.01   816.4  886.85
   845.9  883.12   924.6  864.15  1003.3  853.34  1052.2  843.49    1101  840.23
  1130.3   835.3    1189  828.21  1208.5  822.66  1247.6  805.54  1257.3   802.5
  1267.1  801.02  1276.9   800.7  1530.9   801.3  1540.7  803.43  1609.1  834.64
  1706.1   871.7  1801.6  900.79  1849.3  911.24  1916.1  928.79  1973.4  941.91
#Mann= 3 , 0 , 0
       0      .1       0  1267.1    .033       0  1530.9      .1       0
Bank Sta=1267.1,1530.9
XS Rating Curve= 0 ,0
Exp/Cntr=0.3,0.1

Type RM Length L Ch R = 1 ,6371.5  ,400.8,400,399.2
XS GIS Cut Line= 4
     1868121.673      643045.835     1869242.964      642112.188
     1869436.941      641968.355     1869802.427      641697.347
#Sta/Elev= 30
       0 1034.99   195.8  979.58   264.4  953.17   274.2  950.66   293.8  948.15
   352.5  945.88   479.8  948.09   685.5  962.92     754   964.2   891.1  962.99
    1038  947.23  1077.2  939.83  1214.3  909.71  1302.4     894  1390.6  871.95
  1459.1  848.21  1497.7  835.97  1536.4  825.32  1584.7  803.32  1594.3  801.22
  1613.7   800.7  1797.4  801.02  1807.1  802.44  1816.8  806.32  1874.8  837.34
  1903.9  849.87  1942.6  864.24  2029.7  893.31  2068.5  903.21  2155.6  919.18
#Mann= 3 , 0 , 0
       0      .1       0  1594.3    .033       0  1797.4      .1       0
Bank Sta=1594.3,1797.4
XS Rating Curve= 0 ,0
Exp/Cntr=0.3,0.1

Type RM Length L Ch R = 1 ,5971.5  ,466.5,461.5,456.6
XS GIS Cut Line= 4
     1868547.367      643168.347     1869474.957      642449.578
     1869684.314      642282.108     1870039.623      641997.889
#Sta/Elev= 30
       0 1047.39    39.1 1041.27   127.1 1023.03   195.6 1010.11   459.6  965.03
   547.6  945.89   616.1  939.56   762.8  930.29   880.1  918.89   899.7  916.29
     929  911.02   987.7  903.58  1007.2  900.12  1026.8  895.67  1114.8  872.23
  1134.4  865.15  1278.8  808.41    1298   802.1  1307.5  800.87  1317.1   800.7
  1528.7  801.17  1538.4   802.4  1557.8  809.08  1596.5  824.16  1683.6  861.08
  1712.6   872.7  1741.7  883.35  1790.1  899.67  1819.1  907.86  1896.6  924.58
#Mann= 3 , 0 , 0
       0      .1       0  1307.5    .033       0  1528.7      .1       0
Bank Sta=1307.5,1528.7
XS Rating Curve= 0 ,0
Exp/Cntr=0.3,0.1

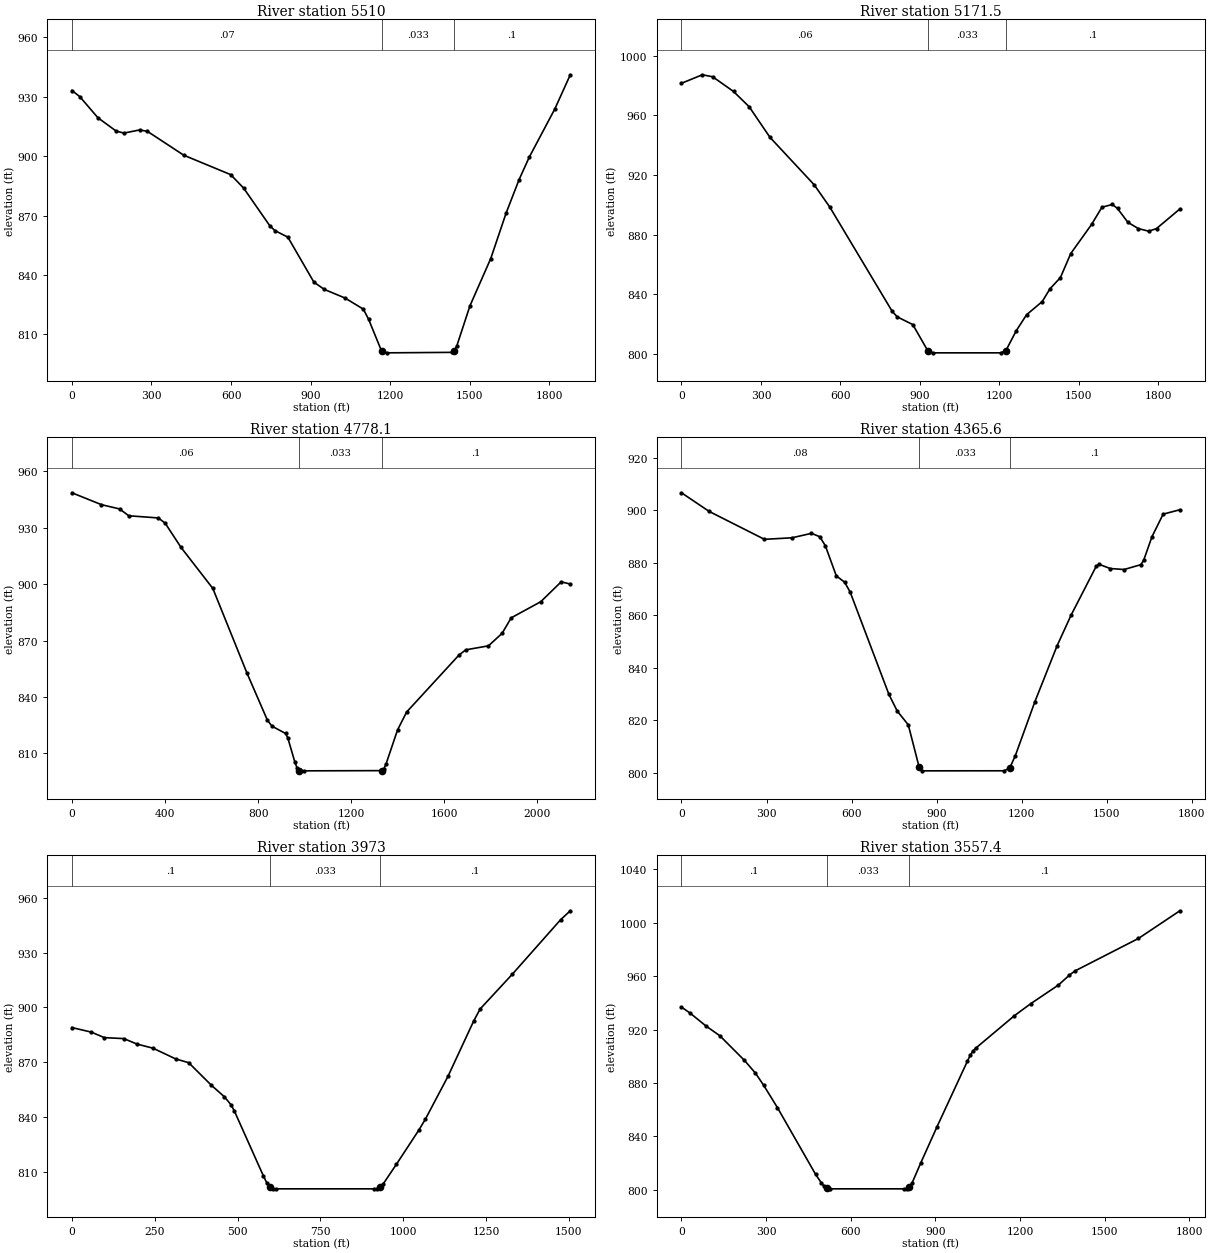
Type RM Length L Ch R = 1 ,5510    ,341.5,338.5,340.6
XS GIS Cut Line= 4
     1869280.874      643732.583     1869675.839      643020.778
     1870166.291      642408.798     1870348.582      642196.125
#Sta/Elev= 30
       0  933.18    29.4  930.13    98.1  919.41   166.7   912.7   196.2  911.67
     255  913.26   284.4  912.57   421.7   900.5   598.3   890.7   647.3  883.89
   745.4  864.96     765  862.44     814  859.12   912.1  836.39   951.3  832.74
  1029.7  828.36  1098.3  822.78  1117.9  817.77    1167  801.65  1186.6   800.7
  1431.6  800.94  1441.4  801.79  1451.2   804.4  1500.3  824.46  1578.7  848.34
  1636.9  871.41  1685.2  888.09  1723.9  899.55  1820.4  923.93  1878.4  941.12
#Mann= 3 , 0 , 0
       0     .07       0    1167    .033       0  1441.4      .1       0
Bank Sta=1167,1441.4
XS Rating Curve= 0 ,0
Exp/Cntr=0.3,0.1

Type RM Length L Ch R = 1 ,5171.5  ,388,393.3,393.5
XS GIS Cut Line= 4
      1869680.18      643671.819     1870131.499      643052.854
     1870286.544      642794.475     1870852.055      642209.146
#Sta/Elev= 30
       0  981.52    78.6  987.22   117.8  985.88   196.4  976.02   255.3  965.82
   333.9  945.27   500.9  913.43   559.8  898.47   795.2  828.57   814.6   824.8
     873  819.67   931.3  801.61   950.7   800.7  1204.6   800.7  1224.3  802.14
  1263.5   815.5  1302.7  826.28  1361.5  835.06    1391  843.67  1430.2  851.14
  1469.4  867.32  1547.8  886.79  1587.1  898.38  1626.3  900.23  1645.9  897.53
  1685.1  888.21  1724.4  884.06  1763.6  882.29    1793  884.06  1881.2  897.21
#Mann= 3 , 0 , 0
       0     .06       0   931.3    .033       0  1224.3      .1       0
Bank Sta=931.3,1224.3
XS Rating Curve= 0 ,0
Exp/Cntr=0.3,0.1

Type RM Length L Ch R = 1 ,4778.1  ,396.7,412.5,428.4
XS GIS Cut Line= 4
     1869762.645      643719.562      1870474.45      643155.326
     1870784.772      642840.783     1871529.138      642573.729
#Sta/Elev= 30
       0  948.65     127  942.33   205.1  940.04   244.2  936.42   371.1  935.26
   400.4  932.53   468.8  919.58   605.5  897.74     752  852.74   839.9  827.64
   859.5  824.47   918.1  820.57     928  818.02   957.4  805.54   967.2  802.26
     977  800.85   996.7   800.7  1330.5  800.81  1340.4  801.86  1350.2  804.58
    1399  822.48    1438     832  1662.6  862.27  1691.9  865.08  1789.5  867.21
  1848.1  873.86  1887.1   882.1  2014.1  890.68  2101.9  901.26    2141  900.09
#Mann= 3 , 0 , 0
       0     .06       0     977    .033       0  1330.5      .1       0
Bank Sta=977,1330.5
XS Rating Curve= 0 ,0
Exp/Cntr=0.3,0.1

Type RM Length L Ch R = 1 ,4365.6  ,393.2,392.6,392
XS GIS Cut Line= 4
     1869884.173      643793.347       1870586.6      643410.135
     1870904.138      643381.021     1871542.159      643337.618
#Sta/Elev= 30
       0  906.73    97.6  899.62   292.7  888.98   390.3  889.57   458.6  891.26
   487.9  889.98   507.4  886.57   546.4  875.03   575.7  872.63   595.2  868.85
   731.8  829.87   761.1  823.52   800.2  818.25   838.8     802   848.5   800.7
  1138.7  800.72  1158.4  801.84  1178.1  806.54  1246.9  827.05  1325.6  848.47
  1374.8   860.1  1463.4  878.71  1473.2  879.47  1512.6  877.85  1561.8  877.47
  1620.8  879.32  1630.6  880.94  1660.1  889.99  1699.5  898.58  1758.5  900.26
#Mann= 3 , 0 , 0
       0     .08       0   838.8    .033       0  1158.4      .1       0
Bank Sta=838.8,1158.4
XS Rating Curve= 0 ,0
Exp/Cntr=0.3,0.1

Type RM Length L Ch R = 1 ,3973    ,418.2,415.6,412.5
XS GIS Cut Line= 4
     1870053.443      644127.548     1870603.765      643807.047
      1870934.52      643767.305     1871464.034      643693.521
#Sta/Elev= 30
       0  888.98    58.8  886.47      98  883.47   156.8  882.93     196  879.97
   244.9  877.68   313.5   871.8   352.7  869.74   421.3  857.36   460.5  851.06
   480.1  846.78   489.9  843.53   578.1  807.79   587.9  804.14   597.7  801.65
   607.4  800.75   617.2   800.7   911.2   800.7     921   800.8   930.8  801.63
   940.6  803.61   979.7  814.14  1047.8  832.96  1067.2  838.85  1135.2   862.2
    1213  892.56  1232.4  899.14  1329.6  918.17  1475.4     948  1504.6   952.9
#Mann= 3 , 0 , 0
       0      .1       0   597.7    .033       0   930.8      .1       0
Bank Sta=597.7,930.8
XS Rating Curve= 0 ,0
Exp/Cntr=0.3,0.1

Type RM Length L Ch R = 1 ,3557.4  ,406.4,415.9,425.8
XS GIS Cut Line= 4
     1870344.242      644414.007      1870773.93      644210.014
     1871134.173      644118.868     1872049.971      644040.743
#Sta/Elev= 30
       0  936.77    29.1  932.53    87.4  922.55   135.9  915.35   223.3  896.86
   262.1  887.35   291.2  878.27   339.8   861.6   475.6  811.45   495.2  805.33
     505  802.76   514.8  801.14   524.6   800.7   788.6   800.7   798.4  800.79
   808.1  801.92   817.9  805.36   847.2   819.7   905.9   847.3  1013.5  896.36
  1023.2  900.61    1033   903.9  1042.8  906.02  1179.7  930.31  1238.4  939.44
  1336.1  953.33  1375.2   960.8  1394.8  963.88  1619.7  988.21  1766.4 1008.92
#Mann= 3 , 0 , 0
       0      .1       0   514.8    .033       0   808.1      .1       0
Bank Sta=514.8,808.1
XS Rating Curve= 0 ,0
Exp/Cntr=0.3,0.1

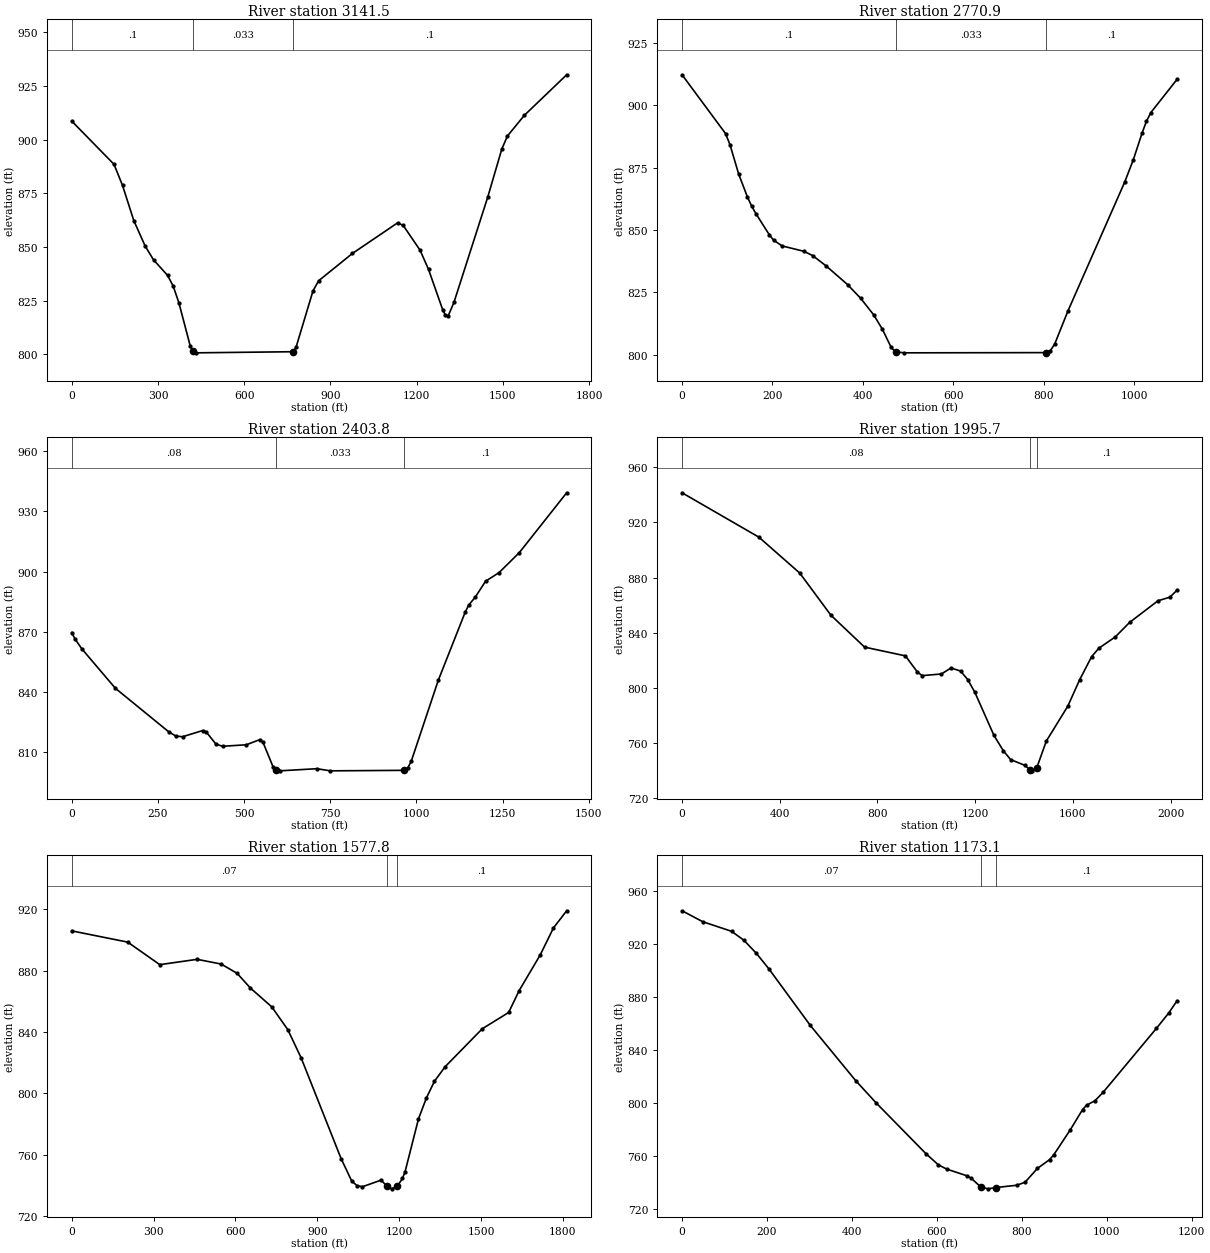
Type RM Length L Ch R = 1 ,3141.5  ,362.5,370.5,378.5
XS GIS Cut Line= 4
     1870422.367      644544.215     1870873.756      644552.896
     1871129.832      644600.639      1872117.68      644811.576
#Sta/Elev= 30
       0  908.67   147.2  888.51   176.7  878.71   215.9  862.34   255.2  850.53
   284.6  844.03   333.7  836.76   353.3  831.71     373  823.95   412.2  803.96
     422  801.36   431.8   800.7   770.8  801.22   780.6  803.34   839.4  829.55
   859.1  834.28   976.8  847.02  1133.7  861.24  1153.3  860.06  1212.1   848.5
  1241.5  839.53  1290.6  820.84  1300.4  818.16  1310.2  818.03  1329.8  824.16
  1447.5  873.27  1496.5  895.67  1516.1  901.74    1575  911.37  1722.1  930.24
#Mann= 3 , 0 , 0
       0      .1       0     422    .033       0   770.8      .1       0
Bank Sta=422,770.8
XS Rating Curve= 0 ,0
Exp/Cntr=0.3,0.1

Type RM Length L Ch R = 1 ,2770.9  ,374.3,367.2,360.1
XS GIS Cut Line= 4
     1870293.895      644679.632     1870712.496        644824.8
     1871015.249      645005.153     1871265.235      645169.752
#Sta/Elev= 30
       0  912.32    96.3  888.69     106  884.25   125.2  872.48   144.5  863.29
   154.1  859.54   163.7  856.47   192.6   848.2   202.3  845.94   221.5  843.61
   269.7  841.45     289  839.72   317.8  835.72     366  828.11   394.9  822.62
   423.8  815.97   443.1  810.18   462.6  802.86   472.4  801.08     492   800.7
   805.1  800.79   814.8  801.62   824.4  804.29   853.4  817.45   978.9  869.16
   998.2  878.23  1017.5  888.91  1027.2  893.64  1036.8  897.12  1094.8  910.46
#Mann= 3 , 0 , 0
       0      .1       0   472.4    .033       0   805.1      .1       0
Bank Sta=472.4,805.1
XS Rating Curve= 0 ,0
Exp/Cntr=0.3,0.1

Type RM Length L Ch R = 1 ,2403.8  ,408.4,408.1,407.4
XS GIS Cut Line= 4
     1869926.707      645127.548      1870528.27      645179.632
      1870747.02      645229.111      1871340.77      645359.319
#Sta/Elev= 30
       0  869.63     9.7  866.39    29.2  861.53   126.6  841.85   282.4  820.02
   301.9  818.06   321.4  817.69   379.8  820.78   389.6  820.22   418.8  813.95
   438.2  812.95   506.4  813.68   545.4  816.24   555.1  814.87   584.3  802.62
   594.1  800.92   603.8   800.7   711.1  801.77   750.1   800.7   965.4  800.95
   975.2  802.22     985  805.44  1063.4  845.79  1141.8  879.88  1151.6  883.27
  1171.2  887.39  1200.6   895.2  1239.9  899.51  1298.7  909.49    1436   939.3
#Mann= 3 , 0 , 0
       0     .08       0   594.1    .033       0   965.4      .1       0
Bank Sta=594.1,965.4
XS Rating Curve= 0 ,0
Exp/Cntr=0.3,0.1

Type RM Length L Ch R = 1 ,1995.7  ,417.9,417.8,417.3
XS GIS Cut Line= 4
     1869239.728       645365.28     1870316.117      645545.835
      1870899.45      645663.891     1871231.395      645736.923
#Sta/Elev= 30
       0  941.58   314.6  909.33   481.8  883.26   609.6   852.6   747.3  829.45
   914.4   823.1   963.6  811.33   983.3  808.74  1061.9  809.95  1101.2  814.29
  1140.2  812.06  1169.5  805.91  1198.8  796.63  1276.8  765.38  1315.8  754.04
  1345.1  747.77  1403.6  743.54  1423.2  740.49  1432.9  739.57  1452.4   741.8
  1491.4   761.2  1579.3  786.53    1628  805.77  1676.8  822.49    1706  828.58
    1774  836.89  1832.2  847.36  1948.8  863.16  1997.3  865.72  2026.5  870.79
#Mann= 3 , 0 , 0
       0     .08       0  1423.2    .045       0  1452.4      .1       0
Bank Sta=1423.2,1452.4
XS Rating Curve= 0 ,0
Exp/Cntr=0.3,0.1

Type RM Length L Ch R = 1 ,1577.8  ,405,404.7,401.4
XS GIS Cut Line= 4
     1869323.062      646059.724     1870080.006      645906.947
     1870732.784      646031.947     1871095.978      646132.757
#Sta/Elev= 30
       0  905.88   205.3  898.54   322.6  883.85   459.4  887.32   547.4  884.26
     606   878.2   654.9  868.58   733.1  856.33   791.8  841.47   840.6  823.13
   987.2  757.37  1026.3  742.66  1045.9  739.76  1065.4  739.06  1133.8  743.36
  1155.1  739.41    1173  737.68  1192.5  739.27    1212  744.44  1221.8  748.98
  1270.7  783.27    1300  797.02  1329.3  807.84  1368.4  817.31  1504.5  842.05
  1601.2  852.68  1639.8  866.97  1717.1  890.27  1765.4  907.82  1813.8  918.98
#Mann= 3 , 0 , 0
       0     .07       0  1155.1    .045       0  1192.5      .1       0
Bank Sta=1155.1,1192.5
XS Rating Curve= 0 ,0
Exp/Cntr=0.3,0.1

Type RM Length L Ch R = 1 ,1173.1  ,423.1,416.4,409.1
XS GIS Cut Line= 4
     1869741.812      646367.132      1870325.88      646366.414
     1870567.332      646393.173     1870905.105      646413.673
#Sta/Elev= 30
       0  945.13    48.7  936.88   116.8  929.61     146  922.76   175.2  912.92
   204.4  901.32   301.8  858.67   408.8  816.94   457.5  799.94   574.3  761.78
   603.5  753.37   622.9  750.18   671.5  745.03   681.2  743.18   703.1   736.7
   720.1  735.26   739.5  736.26   788.1  737.97   807.6  740.23   836.7  750.66
   865.7  757.38   875.3  760.99     914  779.75     943  795.07   952.7  798.48
     972  801.69   991.4   808.1    1117   856.4  1146.1  868.06  1165.4  877.14
#Mann= 3 , 0 , 0
       0     .07       0   703.1    .045       0   739.5      .1       0
Bank Sta=703.1,739.5
XS Rating Curve= 0 ,0
Exp/Cntr=0.3,0.1

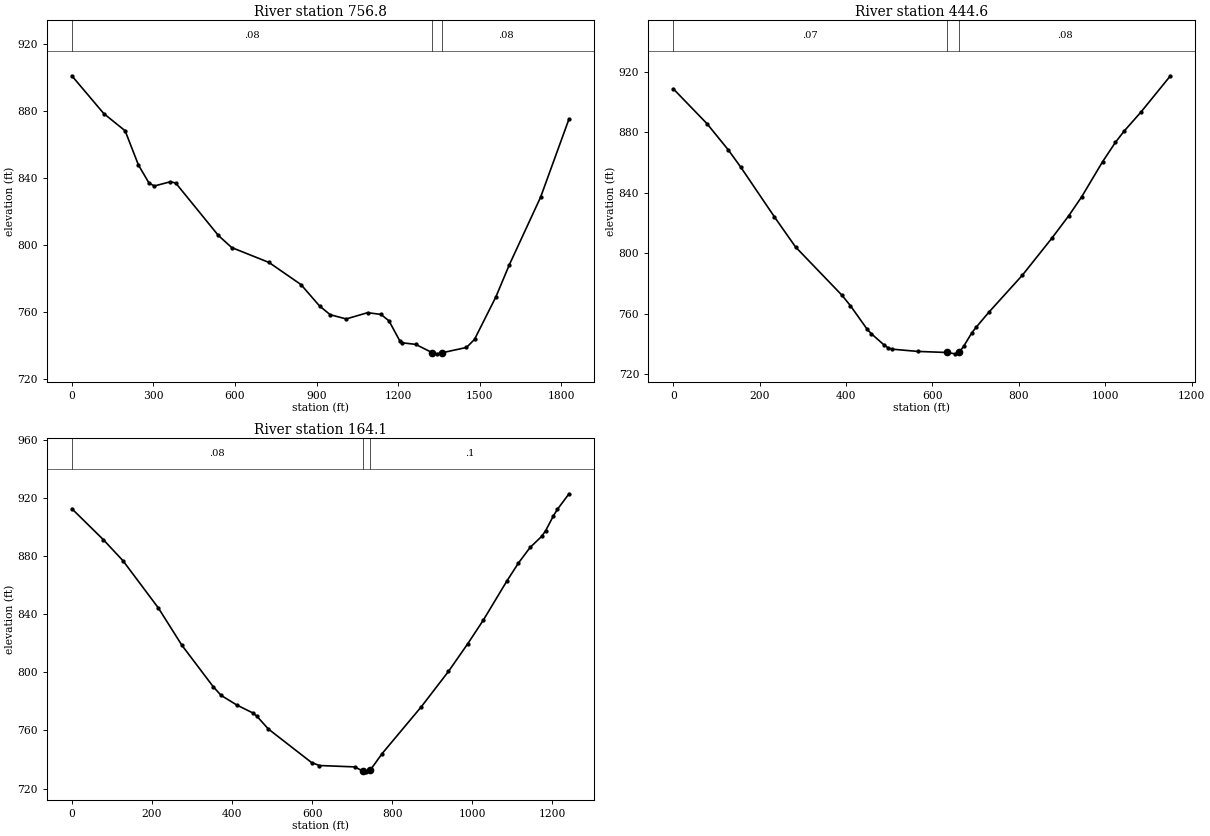
Type RM Length L Ch R = 1 ,756.8   ,318,312.2,306.3
XS GIS Cut Line= 4
     1869095.631       647155.21     1870163.339      646827.085
     1870684.173      646722.919     1870864.115      646709.159
#Sta/Elev= 30
       0  901.23   117.6  878.61     196  868.33     245  847.85   284.2  836.97
   303.7  835.33   362.5  837.87   382.1  837.09   538.9  805.74   587.9  798.52
   725.1   789.6   842.6   776.4   911.2  763.55   950.4  758.34  1009.2  755.82
  1087.6  759.57  1136.7  758.54  1166.2  754.71  1205.5  742.93  1215.4  741.55
  1264.5  740.62  1325.3  735.66  1343.2  734.96  1362.9  735.65  1451.4  738.77
  1480.9  743.59  1559.6  769.04  1608.8  788.15  1724.1  828.69  1828.6  875.47
#Mann= 3 , 0 , 0
       0     .08       0  1325.3    .045       0  1362.9     .08       0
Bank Sta=1325.3,1362.9
XS Rating Curve= 0 ,0
Exp/Cntr=0.3,0.1

Type RM Length L Ch R = 1 ,444.6   ,277.4,280.6,283.9
XS GIS Cut Line= 4
     1869929.312      647312.444     1870379.832      647124.944
     1870658.478      646989.528     1870978.791       646841.09
#Sta/Elev= 30
       0  908.78    78.1   885.7   126.9  868.53   156.2  856.98   234.2  824.06
     283  804.18   390.4  772.28   409.9   765.4   448.9  749.72   458.7  746.73
     488  739.36   497.7  737.41   507.3  736.58   565.4  735.12   633.2   734.4
   652.6  733.51   662.2  734.71   671.9  738.38   691.3  747.52     701  751.06
     730  760.89   807.6  785.36   876.2  809.95   915.5  824.88   944.9  837.17
   993.9  860.66  1023.3   873.3    1043  880.61  1082.2  893.29  1150.8  917.38
#Mann= 3 , 0 , 0
       0     .07       0   633.2    .045       0   662.2     .08       0
Bank Sta=633.2,662.2
XS Rating Curve= 0 ,0
Exp/Cntr=0.3,0.1

Type RM Length L Ch R = 1 ,164.1   ,159,164.1,168.8
XS GIS Cut Line= 4
     1869931.916      647357.583     1870569.068      647326.333
      1870773.93      647260.361     1871064.728      647002.548
#Sta/Elev= 30
       0  912.56    78.5   891.3   127.6   876.8   215.9  844.33   274.8  818.62
   353.3     790   372.9  784.08   412.2  777.44   451.4   772.1   461.3  770.04
   490.7  760.98   598.7  737.88   618.3  735.83   706.4  734.88     726  732.13
   735.8  731.48   745.5  732.74   774.9  744.02   872.6  776.19   940.6  800.56
   989.2  819.79    1028  836.02  1086.3   862.7  1115.5  875.21  1144.6  885.91
  1173.8   893.6  1183.5  897.52  1202.9  907.71  1212.6  912.08  1241.8  922.83
#Mann= 3 , 0 , 0
       0     .08       0     726    .045       0   745.5      .1       0
Bank Sta=726,745.5
XS Rating Curve= 0 ,0
Exp/Cntr=0.3,0.1

Chan Stop Cuts=-1
Use User Specified Reach Order=0
Composite Channel Slope=5